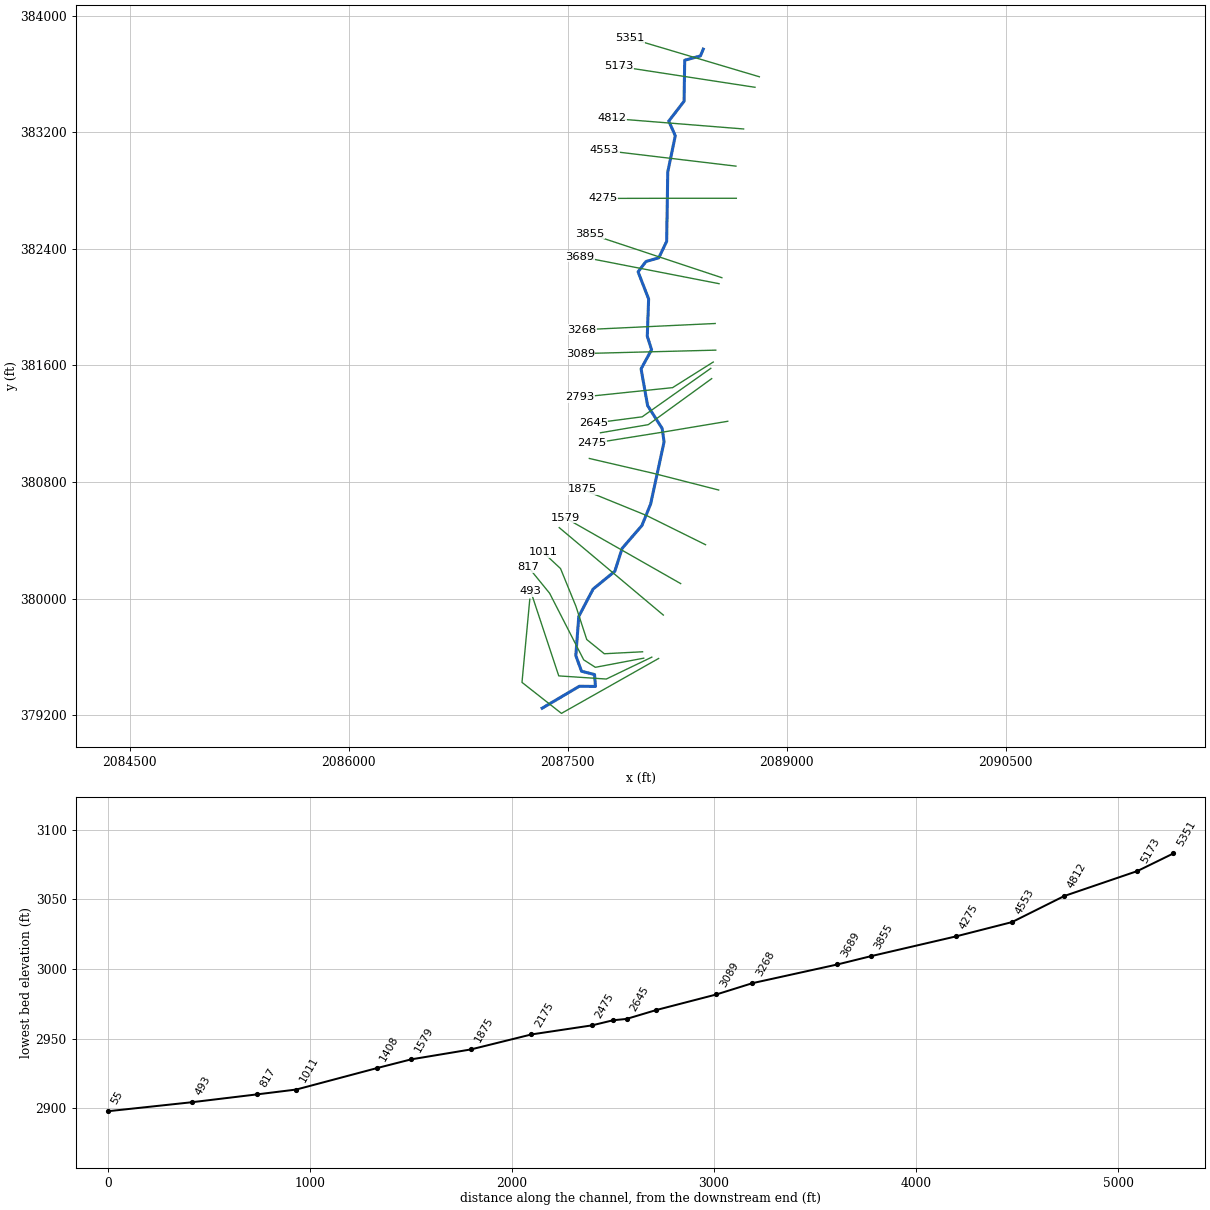
--- SMKHSEBR.prj (project) ---

Proj Title=SMKHSEBR
Current Plan=p01
Default Exp/Contr=0,0
English Units
Geom File=g01
Flow File=f01
Plan File=p01
BEGIN DESCRIPTION:
Stream Name- Smokehouse Branch
Flood Zone: Zone A
Greenbrier County, WV
County-Wide Study
WVDHSEM-2018-3, Flood Risk Project
HEC-RAS Version: 5.0.7
General Notes:
For the Hydrology  regression was used.
END DESCRIPTION:
DSS Export Rating Curves= 0
DSS Export Rating Curve Sorted= 0
DSS Export Volume Flow Curves= 0
DXF OffsetX= 0
DXF OffsetY= 0
DXF ScaleX= 0
DXF ScaleY= 0

--- SMKHSEBR.p01 (plan) ---

Plan Title=Floodplain
Program Version=5.07
Short Identifier=Floodplain
Geom File=g01
Flow File=f01
Subcritical Flow
K Sum by GR= 0
Std Step Tol= 0.01
Critical Tol= 0.01
Num of Std Step Trials= 20
Max Error Tol= 0.3
Flow Tol Ratio= 0.001
Split Flow NTrial= 30
Split Flow Tol= 0.02
Split Flow Ratio= 0.02
Log Output Level= 0
Friction Slope Method= 1
Unsteady Friction Slope Method= 2
Unsteady Bridges Friction Slope Method= 1
Parabolic Critical Depth
Global Vel Dist= 0 , 0 , 0
Global Log Level= 0
CheckData=True
Encroach Param=-1 ,0,0, 0
Mapping Interval=1HOUR
Computation Time Step Use Courant=        0
Computation Time Step Use Time Series=    0
Computation Time Step Count To Double=0
Computation Time Step Max Doubling=0
Computation Time Step Max Halving=0
Computation Time Step Residence Courant=0
Run HTab= 0
Run UNet= 0
Run Sediment= 0
Run PostProcess= 0
Run WQNet= 0
Run RASMapper=-1
UNET Theta= 0
UNET Theta Warmup= 0
UNET ZTol= 0
UNET ZSATol= 0
UNET MxIter= 0
UNET Max Iter WO Improvement= 0
UNET MaxInSteps= 0
UNET DtIC= 0
UNET DtMin= 0
UNET MaxCRTS= 0
UNET WFStab= 0
UNET SFStab= 0
UNET WFX= 1
UNET SFX= 1
UNET 1D Methodology=Finite Difference
UNET DSS MLevel= 1
UNET Pardiso=0
UNET DZMax Abort= 0
UNET Use Existing IB Tables= 0
UNET Froude Reduction=False
UNET Froude Limit= 0
UNET Froude Power= 0
UNET D1 Cores= 0
UNET D2 Coriolis=0
UNET D2 Cores= 0
UNET D2 Theta= 1
UNET D2 Theta Warmup= 1
UNET D2 Z Tol= 0.01
UNET D2 Volume Tol= 0.01
UNET D2 Max Iterations= 20
UNET D2 Equation= 0
UNET D2 RampUpFraction=0.1
UNET D2 TimeSlices= 1
UNET D2 BCVolumeCheck=0
UNET D1D2 MaxIter= 0
UNET D1D2 ZTol=0.01
UNET D1D2 QTol=0.1
UNET D1D2 MinQTol=1
Write IC File= 0
Write IC File at Fixed DateTime=0
Write IC File at Sim End=0
Echo Input=False
Echo Parameters=False
Echo Output=False
Write Detailed= 0
HDF Write Warmup=0
HDF Write Time Slices=0
HDF Flush=0
HDF Face Node Velocities=0
HDF Compression= 1
HDF Chunk Size= 1
HDF Spatial Parts= 1
HDF Use Max Rows=0
HDF Fixed Rows= 1
Calibration Method= 0
Calibration Iterations= 20
Calibration Max Change=0.05
Calibration Tolerance=0.2
Calibration Maximum=1.5
Calibration Minimum=0.5
Calibration Optimization Method= 1
WQ AD Non Conservative
WQ ULTIMATE=-1
WQ Max Comp Step=1HOUR
WQ Output Interval=15MIN
WQ Output Selected Increments= 0
WQ Output face flow=0
WQ Output face velocity=0
WQ Output face area=0
WQ Output face dispersion=0
WQ Output cell volume=0
WQ Output cell surface area=0
WQ Output cell continuity=0
WQ Output cumulative cell continuity=0
WQ Output face conc=0
WQ Output face dconc_dx=0
WQ Output face courant=0
WQ Output face peclet=0
WQ Output face adv mass=0
WQ Output face disp mass=0
WQ Output cell mass=0
WQ Output cell source sink temp=0
WQ Output nsm pathways=0
WQ Output nsm derived pathways=0
WQ Output MaxMinRange=-1
WQ Daily Max Min Mean=-1
WQ Daily Range=0
WQ Daily Time=0
WQ Create Restart=0
WQ Fixed Restart=0
WQ System Summary=0
WQ Write To DSS=0
WQ Use Fixed Temperature=0
Sorting and Armoring Iterations= 10
XS Update Threshold= 0.02
Bed Roughness Predictor= 0
Hydraulics Update Threshold= 0.02
Energy Slope Method= 1
Volume Change Method= 1
Sediment Retention Method= 0
XS Weighting Method= 0
Number of US Weighted Cross Sections= 1
Number of DS Weighted Cross Sections= 1
Upstream XS Weight=0
Main XS Weight=1
Downstream XS Weight=0
Number of DS XS's Weighted with US Boundary= 1
Upstream Boundary Weight= 1
Weight of XSs Associated with US Boundary= 0
Number of US XS's Weighted with DS Boundary= 1
Downstream Boundary Weight= 0.5
Weight of XSs Associated with DS Boundary= 0.5
Percentile Method= 0
Sediment Output Level= 3
Mass or Volume Output= 0
Output Increment Type= 1
Profile and TS Output Increment= 1
XS Output Flag= 0
XS Output Increment= 10
Write Gradation File= 0
Read Gradation Hotstart= 0
Write HDF5 File= 1
Write Binary Output= 1
Write DSS Sediment File= 0
SV Curve= 0
Specific Gage Flag= 0

--- SMKHSEBR.f01 (steady flow) ---

Flow Title=H3a_CombinedFlows
Program Version=5.07
Number of Profiles= 6
Profile Names=f1p,f10p,f4p,f2p,f02p,f1pplus
River Rch & RM=SMKHSEBR,Main            ,5351
     564     298     396     478     788     835
River Rch & RM=SMKHSEBR,Main            ,2475
     672     358     474     570     937     995
Boundary for River Rch & Prof#=SMKHSEBR,Main            , 1
Up Type= 0
Dn Type= 3
Dn Slope=0.01548
Boundary for River Rch & Prof#=SMKHSEBR,Main            , 2
Up Type= 0
Dn Type= 3
Dn Slope=0.01548
Boundary for River Rch & Prof#=SMKHSEBR,Main            , 3
Up Type= 0
Dn Type= 3
Dn Slope=0.01548
Boundary for River Rch & Prof#=SMKHSEBR,Main            , 4
Up Type= 0
Dn Type= 3
Dn Slope=0.01548
Boundary for River Rch & Prof#=SMKHSEBR,Main            , 5
Up Type= 0
Dn Type= 3
Dn Slope=0.01548
Boundary for River Rch & Prof#=SMKHSEBR,Main            , 6
Up Type= 0
Dn Type= 3
Dn Slope=0.01548
DSS Import GetInterval= 0
DSS Import GetPeak= 0
DSS Import FillOption= 0

--- SMKHSEBR.g01 (geometry) ---

Geom Title=Geometry
Program Version=5.07

River Reach=SMKHSEBR        ,Main
Reach XY= 30
2088428.65372076383769.746498164  2088409.044067 383723.08743028
     2088301.479      383693.604     2088297.063       383412.13
      2088192.37      383276.132     2088236.995        383175.4
     2088185.361      382926.938     2088177.879      382450.631
     2088123.623      382337.926     2088035.994      382312.732
     2087982.086      382242.213     2088054.312      382055.826
     2088045.057      381800.062     2088074.619       381707.49
     2088002.568      381576.298     2088047.353      381324.024
     2088147.153      381167.193     2088160.092       381075.26
     2088067.974      380648.446     2088008.241      380501.211
     2087872.724      380344.381     2087822.713      380187.261
     2087674.035      380065.334     2087576.021      379878.156
     2087555.601      379608.651     2087594.813      379501.595
     2087683.904      379478.948     2087690.012      379397.415
     2087579.759      379398.654     2087324.819      379247.976

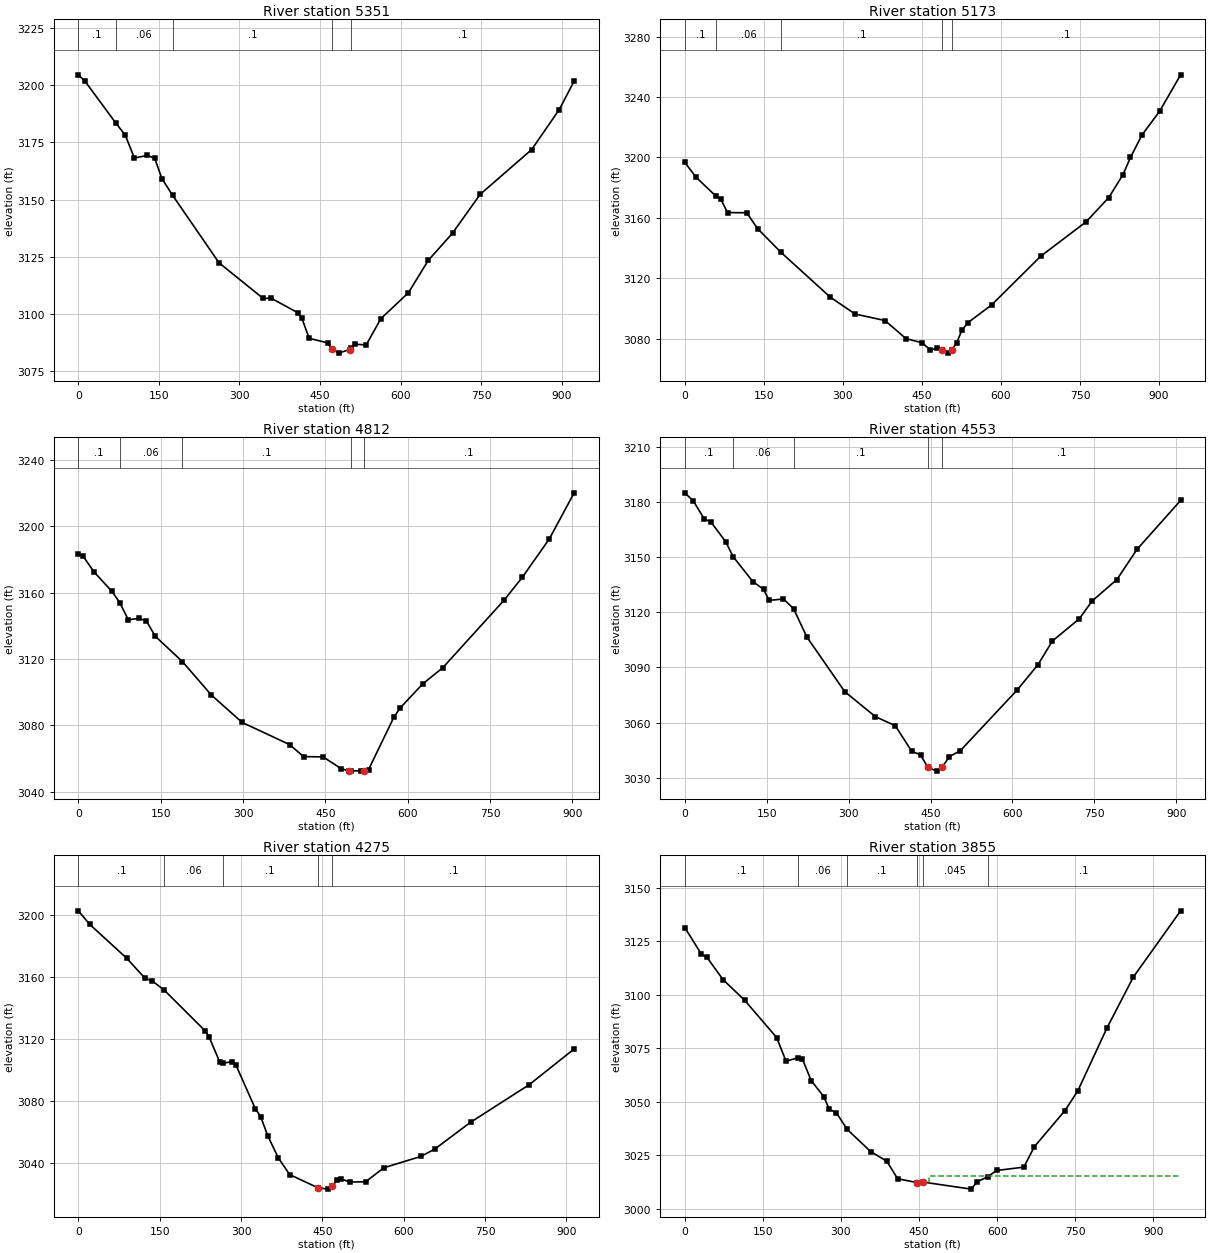
Type RM Length L Ch R = 1 ,5351    ,148.4,178.4,151.1
XS GIS Cut Line= 2
 2088812.6950274383580.1873509822087928.18802118383843.838477836
#Sta/Elev= 30
       0 3204.42      12 3201.75    70.2 3183.25    87.2 3178.16   104.4 3168.11
   128.4 3169.26   142.1 3168.02   155.7 3159.09   175.4 3151.88   261.9 3122.41
   344.1 3106.85   358.8 3106.98   408.9 3100.58     416 3098.33   429.7 3089.46
   463.9 3087.48   472.2 3084.85   484.4    3083     505 3084.58   508.4 3085.42
   515.3 3086.89   535.8 3086.56   563.2 3098.05   614.4 3109.33   651.5 3123.48
   696.7 3135.38     748 3152.27   843.9 3171.81   895.3 3189.28     923  3201.7
#Mann= 5 ,-1 , 0
       0      .1       0    70.2     .06       0   175.4      .1       0
   472.2    .045       0   508.4      .1       0
Bank Sta=472.2,505
XS Rating Curve= 0 ,0
Exp/Cntr=0.3,0.1

Type RM Length L Ch R = 1 ,5173    ,357.4,361.6,360.2
XS GIS Cut Line= 2
 2088782.9569771383508.0200239012087852.89730831383650.931631546
#Sta/Elev= 30
       0 3196.68    21.4 3186.85   59.793174.105    67.9 3172.66    81.1 3163.46
   117.6 3163.33     138  3152.9  182.78 3137.01   276.1 3107.43   323.4 3096.21
   379.9 3091.95   419.7 3079.96   449.6 3077.28   466.2 3072.58   479.4 3073.55
   487.3 3072.11   499.4 3070.34   506.3 3072.12     516 3077.27   525.9 3085.46
   536.9 3090.42   582.3 3102.27   675.3 3134.49   761.6 3157.33   804.7 3173.44
   831.5 3188.52   845.8 3199.96   867.8 3214.94     901 3230.51     941 3254.71
#Mann= 5 ,-1 , 0
       0      .1       0   59.79     .06       0  182.78      .1       0
   487.3    .045       0   506.3      .1       0
Bank Sta=487.3,506.3
XS Rating Curve= 0 ,0
Exp/Cntr=0.3,0.1

Type RM Length L Ch R = 1 ,4812    ,257.4,259.1,257.9
XS GIS Cut Line= 2
2088704.81025612383222.0507824812087804.60456236383294.173459676
#Sta/Elev= 30
       0 3183.29     8.6    3182    28.4 3172.59    61.3 3160.72   75.423154.037
    90.9 3143.73   110.7 3144.44   123.8    3143   140.3 3133.67  189.533118.465
   242.3 3098.31   298.3 3081.81   384.9 3068.42   410.2  3061.2   445.9 3061.01
   479.3 3053.81   493.2 3052.58   495.83052.732   515.5 3052.44   520.7 3052.58
   520.83052.581   528.7 3053.42   574.7 3084.91     586 3090.45   627.4 3105.07
   663.6  3114.7     775 3155.29   808.5 3169.18   857.8 3192.36   903.1 3220.18
#Mann= 5 ,-1 , 0
       0      .1       0   75.42     .06       0  189.53      .1       0
   495.8    .045       0   520.8      .1       0
Bank Sta=493.2,520.7
XS Rating Curve= 0 ,0
Exp/Cntr=0.3,0.1

Type RM Length L Ch R = 1 ,4553    ,275.4,278.1,278.8
XS GIS Cut Line= 2
2088652.52177965382966.9975092482087750.81758856383074.748324535
#Sta/Elev= 30
       0 3184.84    15.5 3180.45    35.3 3170.88    48.5 3168.74      75 3158.26
   88.433150.233   124.5 3136.66   144.3 3132.42   154.3 3126.43   180.7 3127.16
  199.143121.971   223.6 3106.51     293 3076.84   349.2 3063.25   385.5 3058.37
   415.3  3044.6   431.8 3042.48     445  3035.8   461.5 3033.69   471.1 3035.68
   484.7 3041.63   504.5 3044.75   608.4 3077.64   646.6  3091.4   673.3 3104.38
   722.6 3116.43   745.7 3126.01   791.4 3137.75   828.3 3154.16   908.1 3180.71
#Mann= 5 ,-1 , 0
       0      .1       0   88.43     .06       0  199.14      .1       0
     445    .045       0   471.1      .1       0
Bank Sta=445,471.1
XS Rating Curve= 0 ,0
Exp/Cntr=0.3,0.1

Type RM Length L Ch R = 1 ,4275    ,423.2,419.8,415.1
XS GIS Cut Line= 3
     2088655.102       382746.49     2088197.506      382746.479
     2087740.695      382745.577
#Sta/Elev= 30
       0 3202.51    21.2 3193.73      89 3172.07   122.9 3159.12   136.1 3157.43
  158.523151.444   234.5 3125.05     241 3121.47   260.7 3105.26  266.373104.404
   283.7 3105.46   290.3 3103.53   326.3 3075.23   336.2 3070.11   349.3 3057.72
     369 3043.39   389.8 3032.75   441.2 3024.36   460.9  3023.4   468.5 3025.15
   477.3 3029.33   483.8  3030.1   500.2 3027.99   529.8 3028.13   563.5 3037.16
   631.5 3044.42     657 3049.09   723.3 3066.41   831.6 3090.64   914.4 3113.62
#Mann= 5 ,-1 , 0
       0      .1       0  158.52     .06       0  266.37      .1       0
   441.2    .045       0   468.5      .1       0
Bank Sta=441.2,468.5
XS Rating Curve= 0 ,0
Exp/Cntr=0.3,0.1

Type RM Length L Ch R = 1 ,3855    ,166.5,165.7,165.3
XS GIS Cut Line= 2
2088556.00399839382201.5744869082087652.03136909382502.142550604
#Sta/Elev= 30
       0 3131.44      32 3118.95    42.4 3117.56    73.5  3107.1     115 3097.46
   176.5 3080.05   194.5 3069.02  217.24 3070.54   225.7 3070.14   242.9 3059.91
   266.9 3052.49   277.5  3046.6   291.3 3044.85  312.173037.109     357 3026.81
   388.2 3022.25   408.9  3014.1   446.3  3012.3   457.3 3012.54   550.7 3009.24
     561 3012.57   581.8 3015.01   599.1 3017.95   651.3 3019.51   671.7 3029.09
   730.4 3045.94   755.1 3055.17   810.7 3084.34   861.8 3108.32   952.6 3139.25
#Mann= 6 ,-1 , 0
       0      .1       0  217.24     .06       0  312.17      .1       0
   446.3    .045       0   457.3    .045       0   581.8      .1       0
#XS Ineff= 2 , 0
                          468.59         3015.39
Permanent Ineff=
       F       F
Bank Sta=446.3,457.3
XS Rating Curve= 0 ,0
Exp/Cntr=0.3,0.1

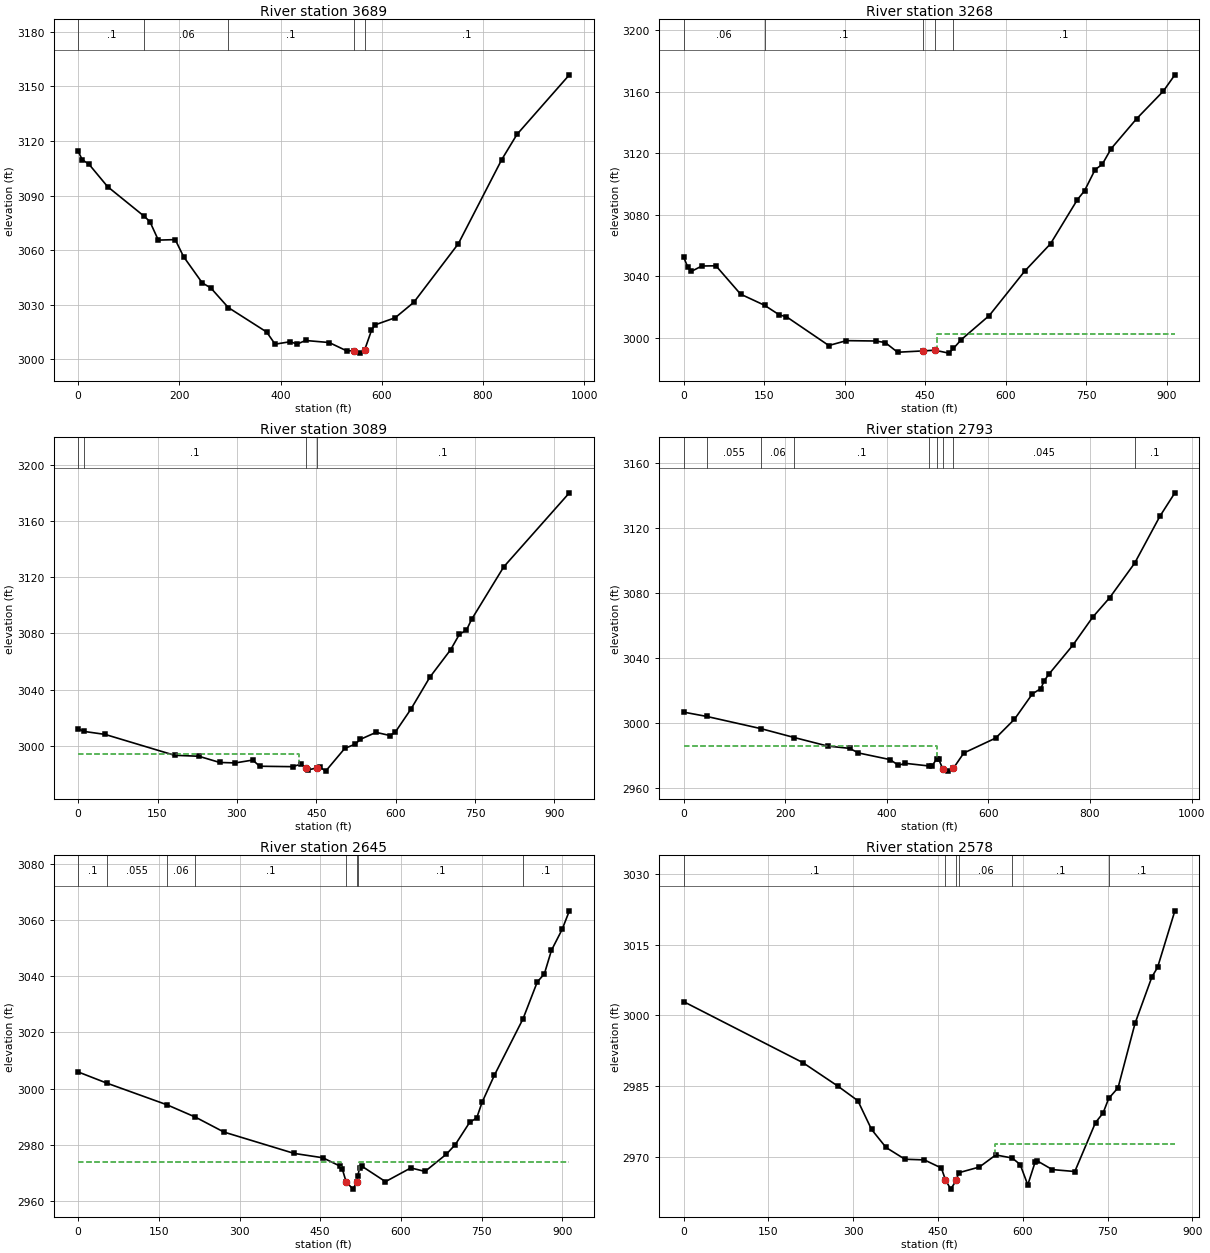
Type RM Length L Ch R = 1 ,3689    ,419.2,421,423.6
XS GIS Cut Line= 2
2088536.83143061382160.5677232542087584.08737964382346.579657014
#Sta/Elev= 30
       0  3114.4     8.1  3109.7    21.5  3107.2    58.2  3094.9  131.053078.476
   141.8 3075.67   158.5 3065.47   191.9 3065.74   208.4 3056.37   245.4  3041.9
   262.1 3039.19  296.753028.374   372.5 3014.92   389.2 3008.23   419.3 3009.58
   432.6 3008.26   449.4 3010.25   496.1 3009.13   530.4 3004.59   544.9 3004.51
   556.3  3003.3   566.3 3005.15   579.7 3015.81   586.4 3018.82   626.5 3022.76
   663.3 3031.25   751.4 3063.52   837.1 3109.79   867.2 3123.63   970.7 3156.39
#Mann= 5 ,-1 , 0
       0      .1       0  131.05     .06       0  296.75      .1       0
   544.9    .045       0   566.3      .1       0
Bank Sta=544.9,566.3
XS Rating Curve= 0 ,0
Exp/Cntr=0.3,0.1

Type RM Length L Ch R = 1 ,3268    ,178.5,178.9,178.2
XS GIS Cut Line= 2
2088510.27380028381887.4177421792087596.42780028381844.396742179
#Sta/Elev= 30
       0 3052.39     7.6 3046.02    14.2 3043.02    33.9 3046.57    60.2 3046.72
   106.1 3028.26  150.683021.022   178.4 3014.72   191.6 3013.53   270.4 2994.81
   303.2 2997.99   357.9 2997.75   375.5 2996.75   398.5 2990.44   446.7 2991.32
   467.9 2991.77   493.7 2989.86   502.6 2992.94     517 2998.61   569.3 3014.35
     635 3043.14   683.3 3061.04   733.5 3089.85   746.6 3095.53   766.4 3109.36
   779.5 3112.67   796.2 3122.97   843.8 3142.52   893.5 3160.46   914.9 3171.04
#Mann= 5 ,-1 , 0
       0     .06       0  150.68      .1       0   446.7    .045       0
   467.9    .045       0   502.6      .1       0
#XS Ineff= 2 , 0
                          470.98         3002.02
Permanent Ineff=
       F       F
Bank Sta=446.7,467.9
XS Rating Curve= 0 ,0
Exp/Cntr=0.3,0.1

Type RM Length L Ch R = 1 ,3089    ,293.9,296.3,295.8
XS GIS Cut Line= 2
2088514.14704844381704.6116417222087586.35581786381680.793040448
#Sta/Elev= 30
       0 3011.88   11.363010.068    50.9 3007.95   182.2 2993.04   228.1 2992.35
   267.5 2987.92     297 2987.59   329.9 2989.63     343 2985.22   405.3 2984.91
   421.8 2986.85   429.7 2983.73   434.9 2982.69   450.4 2983.89   457.9 2984.35
   467.7 2981.73   503.8 2997.97   523.5 3000.98   533.3 3004.43   562.9 3009.41
   589.1 3007.16     599 3009.45     629 3026.15   664.6 3048.85     704 3068.53
   720.4 3079.48   733.7 3082.47   743.4 3090.07   804.1 3127.58   928.1 3180.44
#Mann= 4 ,-1 , 0
       0     .06       0   11.36      .1       0   429.7    .045       0
   450.4      .1       0
#XS Ineff= 2 , 0
          417.15 2993.91
Permanent Ineff=
       F       F
Bank Sta=429.7,450.4
XS Rating Curve= 0 ,0
Exp/Cntr=0.3,0.1

Type RM Length L Ch R = 1 ,2793    ,142.3,147.5,154.8
XS GIS Cut Line= 3
2088496.94437276381622.9891280952088218.33038281381447.338907998
2087584.08737964 381381.35919586
#Sta/Elev= 30
       0  3006.9    45.6 3004.24   152.3 2996.73   218.2 2991.24   283.5 2986.02
   326.8 2984.61     344 2981.79   406.4 2977.69   422.9 2974.19     436 2975.41
   482.2  2973.8   488.8 2973.78   498.6 2978.25     502 2978.06   510.5 2971.68
   519.7  2970.6   531.2 2972.44   551.5 2981.74   614.2 2990.93   651.2 3002.49
   686.7 3018.19   703.2 3021.36   709.8 3026.22   719.5 3030.42   765.9 3047.97
   805.5 3065.42   838.5 3077.22   887.9 3098.57   937.4 3127.33     967 3141.81
#Mann= 9 ,-1 , 0
       0      .1       0    45.6    .055       0   152.3     .06       0
   218.2      .1       0   482.2    .045       0   498.6      .1       0
   510.5    .045       0   531.2    .045       0   887.9      .1       0
#XS Ineff= 2 , 0
          498.75 2986.32
Permanent Ineff=
       F       F
Bank Sta=510.5,531.2
XS Rating Curve= 0 ,0
Exp/Cntr=0.5,0.3

Type RM Length L Ch R = 1 ,2645    ,67.3,67.6,67.6
XS GIS Cut Line= 3
2088480.17734633381579.7558135042088010.24667416381247.220125991
2087675.71975498381203.413029432
#Sta/Elev= 30
       0  3005.9    52.9 3001.95   165.4 2994.19   217.7 2989.85   271.1  2984.5
   401.7  2976.9   454.8 2975.36   486.9 2972.38     491 2971.37   498.3 2966.73
   511.1  2964.2   517.5  2966.7   519.9 2968.96   523.1 2971.66   527.1  2972.4
   571.3 2966.86   618.4 2971.74   644.9  2970.5   684.4 2976.62   701.2 2980.07
   727.6 2987.91   740.9 2989.55   750.8 2995.07   773.9 3004.79   826.9 3024.77
   853.4 3037.89   866.6 3040.79   879.8 3049.17   899.7 3056.63   913.1 3063.22
#Mann= 8 ,-1 , 0
       0      .1       0    52.9    .055       0   165.4     .06       0
   217.7      .1       0   498.3    .045       0   517.5    .045       0
   519.9      .1       0   826.9      .1       0
#XS Ineff= 2 , 0
          488.56    2974  521.77            2974
Permanent Ineff=
       F       F
Bank Sta=498.3,517.5
XS Rating Curve= 0 ,0
Exp/Cntr=0.5,0.3

Type RM Length L Ch R = 1 ,2578    ,106.9,103.1,94.3
XS GIS Cut Line= 3
2088486.15104132381509.0670895122088052.06253906381193.456871124
 2087724.5049307381137.702384595
#Sta/Elev= 30
       0 3002.92   210.8 2990.01   272.8 2985.03   308.2 2981.94   332.5 2975.84
   358.1 2972.03   391.5 2969.54   425.8  2969.4     456 2967.68   463.1 2965.18
   472.5 2963.21   482.6 2965.12   486.4 2966.67   523.2 2967.89   552.2 2970.45
   581.2  2969.8   595.4 2968.42   608.8  2964.1   622.1 2969.06   625.4  2969.2
   652.1 2967.35     692 2966.94   728.6  2977.3   741.9 2979.31     752 2982.42
   768.5 2984.68   798.5  2998.3   828.4 3008.16   838.4 3010.17     869 3022.15
#Mann= 6 ,-1 , 0
       0      .1       0   463.1    .045       0   482.6    .045       0
   486.4     .06       0   581.2      .1       0     752      .1       0
#XS Ineff= 2 , 0
                          551.21         2972.77
Permanent Ineff=
       F       F
Bank Sta=463.1,482.6
XS Rating Curve= 0 ,0
Exp/Cntr=0.5,0.3

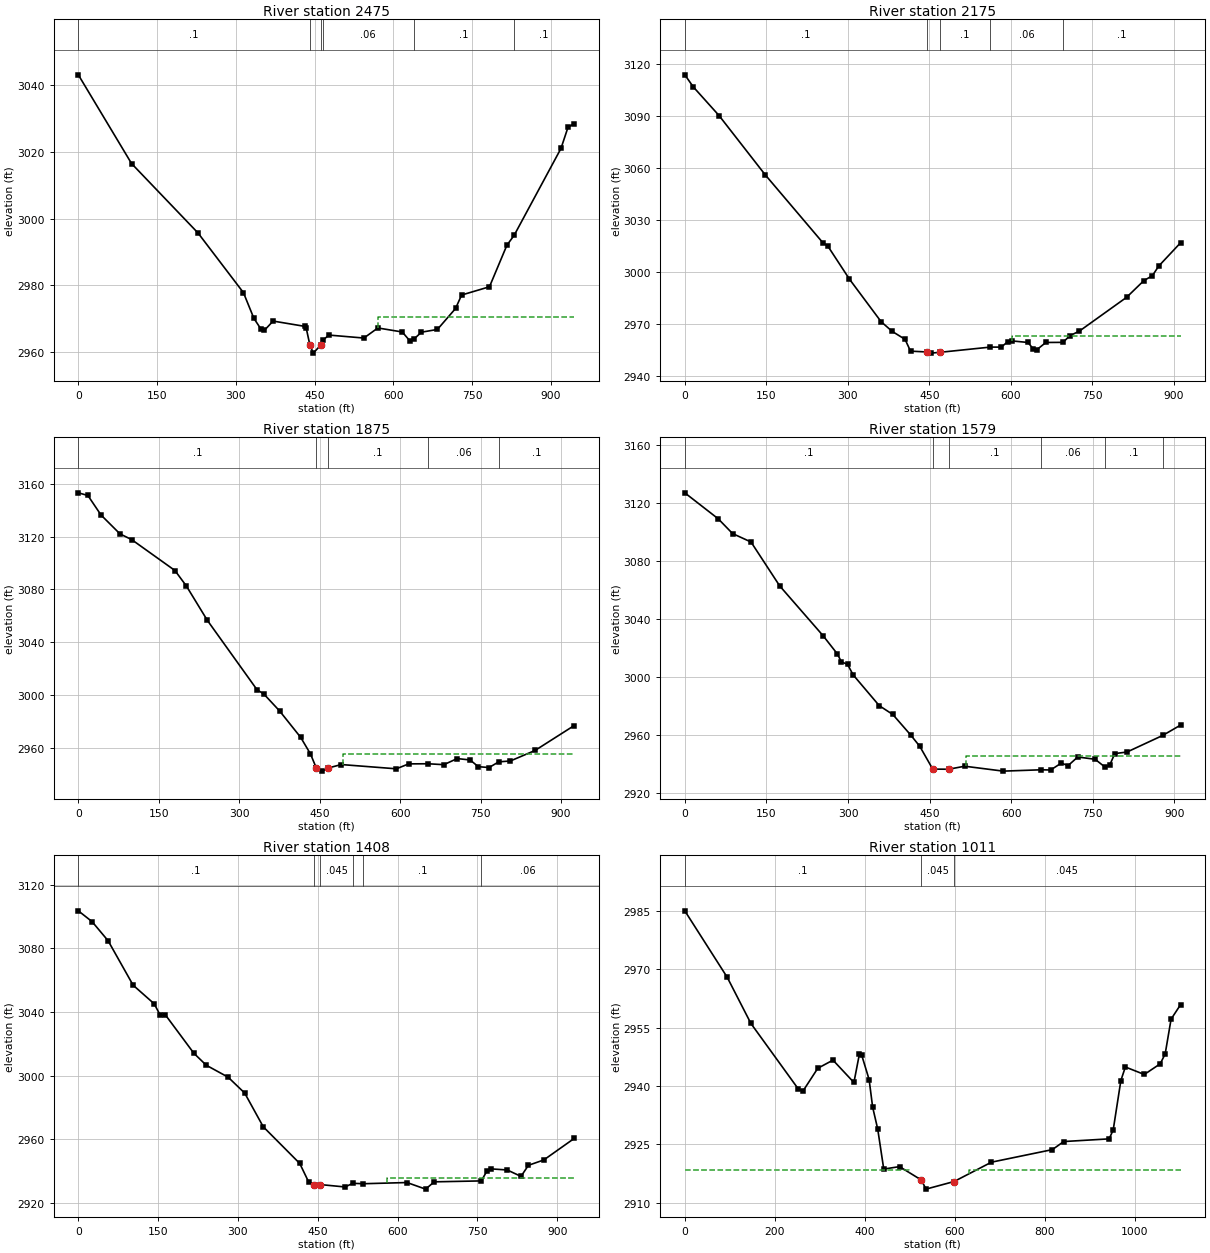
Type RM Length L Ch R = 1 ,2475    ,302.9,300,291.7
XS GIS Cut Line= 3
     2088596.259      381216.591     2088154.832      381142.698
     2087664.283      381064.167
#Sta/Elev= 30
       0 3043.17   101.4 3016.52     228 2995.66   314.5 2977.74   334.4 2970.02
   347.7 2966.84   354.4 2966.43     371 2969.21   430.9 2967.63   434.2 2966.99
   440.9 2962.11   447.5 2959.58   461.3 2961.92  465.762963.469   477.4    2965
   543.9 2964.11   570.5 2967.14     617 2965.93   631.4 2963.28  638.692963.724
   653.5 2965.87   683.9 2966.69   718.5 2972.99     730 2977.03   783.1 2979.51
   816.3 2991.99  830.15 2994.98   919.3 3021.06   932.6 3027.38   944.4 3028.54
#Mann= 6 ,-1 , 0
       0      .1       0   440.9    .045       0   461.3      .1       0
  465.76     .06       0  638.69      .1       0  830.15      .1       0
#XS Ineff= 2 , 0
                           570.9         2970.56
Permanent Ineff=
       F       F
Bank Sta=440.9,461.3
XS Rating Curve= 0 ,0
Exp/Cntr=0.3,0.1

Type RM Length L Ch R = 1 ,2175    ,301.1,300,297.5
XS GIS Cut Line= 3
     2088534.243      380744.932     2088090.895       380858.55
     2087648.221      380961.477
#Sta/Elev= 30
       0 3113.68    15.7 3106.69      63 3090.17   147.8 3056.03   254.4 3016.63
   262.9 3014.95   302.9 2995.76   361.2 2971.19   381.5 2965.62   405.2 2961.02
   415.3  2954.2   445.7 2953.73   452.6 2953.06   469.5 2953.53  562.012956.541
   582.3 2956.53   594.1 2959.66   601.4 2960.13   631.5  2959.2   641.3 2955.37
     648 2955.13   664.3 2959.21  695.832959.275   708.6 2963.18   725.5 2965.67
     813 2985.32   844.6 2994.92   860.2 2997.74     872 3003.34   912.2 3016.78
#Mann= 5 ,-1 , 0
       0      .1       0   445.7    .045       0   469.5      .1       0
  562.01     .06       0  695.83      .1       0
#XS Ineff= 2 , 0
                          601.16         2963.18
Permanent Ineff=
       F       F
Bank Sta=445.7,469.5
XS Rating Curve= 0 ,0
Exp/Cntr=0.3,0.1

Type RM Length L Ch R = 1 ,1875    ,296.1,295.8,295.2
XS GIS Cut Line= 3
     2088444.225      380369.726     2088037.003      380571.561
     2087601.811      380748.904
#Sta/Elev= 30
       0 3153.22    17.8 3151.21    42.3 3136.41    77.6 3122.12    99.6 3117.72
   180.1 3094.34   201.5 3082.56   240.6 3056.52   333.1 3004.01   345.9 3000.72
   375.3 2987.87   414.5  2967.9   432.8 2955.32   443.8 2944.52   443.8  2944.5
   454.8 2942.29   465.4  2944.6   490.2 2947.28   592.9 2944.05   615.9 2947.78
  652.07 2947.87   681.5 2947.18   706.3  2951.8   730.5 2950.75   745.6 2945.67
   765.7    2945  783.712949.308   805.5 2949.99   851.6 2957.98   924.4 2976.82
#Mann= 5 ,-1 , 0
       0      .1       0   443.8    .045       0   465.4      .1       0
  652.07     .06       0  783.71      .1       0
#XS Ineff= 2 , 0
                          493.21         2955.02
Permanent Ineff=
       F       F
Bank Sta=443.8,465.4
XS Rating Curve= 0 ,0
Exp/Cntr=0.3,0.1

Type RM Length L Ch R = 1 ,1579    ,166.6,170.7,162.3
XS GIS Cut Line= 2
2088273.69259748380103.094260818 2087482.0076599380554.513465917
#Sta/Elev= 30
       0 3127.21    61.5 3109.26    87.7 3099.12   121.7 3093.27   174.5 3062.94
   254.1 3028.64   280.3 3016.09   287.8  3010.6   299.2 3008.79   309.3 3001.64
   357.4 2980.33   382.3 2974.25   415.1 2960.12   431.9 2952.26   455.7 2936.55
   484.8 2936.47   514.5 2938.55   585.2 2935.16  654.792936.081   672.4 2935.95
     692  2940.7   704.5 2938.97   722.2 2944.91   754.2 2943.34  772.342937.915
   780.7  2939.1   790.3 2947.25   812.8 2948.35  878.372959.788   911.3 2966.94
#Mann= 6 ,-1 , 0
       0      .1       0   455.7    .045       0   484.8      .1       0
  654.79     .06       0  772.34      .1       0  878.37      .1       0
#XS Ineff= 2 , 0
                          517.17          2945.3
Permanent Ineff=
       F       F
Bank Sta=455.7,484.8
XS Rating Curve= 0 ,0
Exp/Cntr=0.3,0.1

Type RM Length L Ch R = 1 ,1408    ,460.5,397.2,394.2
XS GIS Cut Line= 2
2088154.98338292379887.0341601252087442.00054626380486.939189914
#Sta/Elev= 30
       0 3103.59    25.9 3096.78    55.9 3084.82     103 3056.88   142.6  3045.2
     154 3037.98   163.6 3038.25   217.1 3014.16   240.4 3006.64   281.4 2999.15
   312.6 2989.17   347.5    2968   416.1 2944.95   433.2 2933.07     443 2931.38
   454.6 2931.69   501.2 2930.19   515.8 2932.48   535.8 2932.22   617.7 2932.97
   652.6 2928.83   668.9 2933.41   757.3 2933.99   767.6 2940.04   776.2 2941.54
   806.2 2940.84   831.9 2936.82   845.8 2943.78   874.8 2947.16   931.8 2960.64
#Mann= 6 ,-1 , 0
       0      .1       0     443    .045       0   454.6    .045       0
   515.8    .045       0   535.8      .1       0   757.3     .06       0
#XS Ineff= 2 , 0
                          579.23         2936.08
Permanent Ineff=
       F       F
Bank Sta=443,454.6
XS Rating Curve= 0 ,0
Exp/Cntr=0.5,0.3

Type RM Length L Ch R = 1 ,1011    ,193.8,193.8,193.8
XS GIS Cut Line= 6
2088012.86704542379635.219449333 2087750.7775831379621.675091612
 2087630.4084232379719.2951675562087555.85005567379948.511509317
2087450.96912713380206.0496801432087330.24018107380318.903394529
#Sta/Elev= 30
       0    2985    94.3 2967.92   146.9 2956.07     252 2939.28   262.4 2938.67
   295.5 2944.56   329.3 2946.65   375.8 2940.91   387.9 2948.15   392.9 2948.01
   409.6 2941.66   417.4 2934.59   428.7 2928.94   442.1 2918.67   477.2  2919.3
   525.8 2915.85   535.9 2913.52   598.3 2915.47   681.4 2920.44   816.8 2923.67
     842 2925.74     943 2926.43     952 2928.73     969 2941.41     979 2944.89
  1021.1 2942.97  1056.5 2945.71  1067.5 2948.27  1080.6 2957.18  1101.8 2960.92
#Mann= 3 ,-1 , 0
       0      .1       0   525.8    .045       0   598.3    .045       0
#XS Ineff= 2 , 0
       0  499.15 2918.34   630.6       0 2918.34
Permanent Ineff=
       F       F
Bank Sta=525.8,598.3
XS Rating Curve= 0 ,0
Exp/Cntr=0.5,0.3

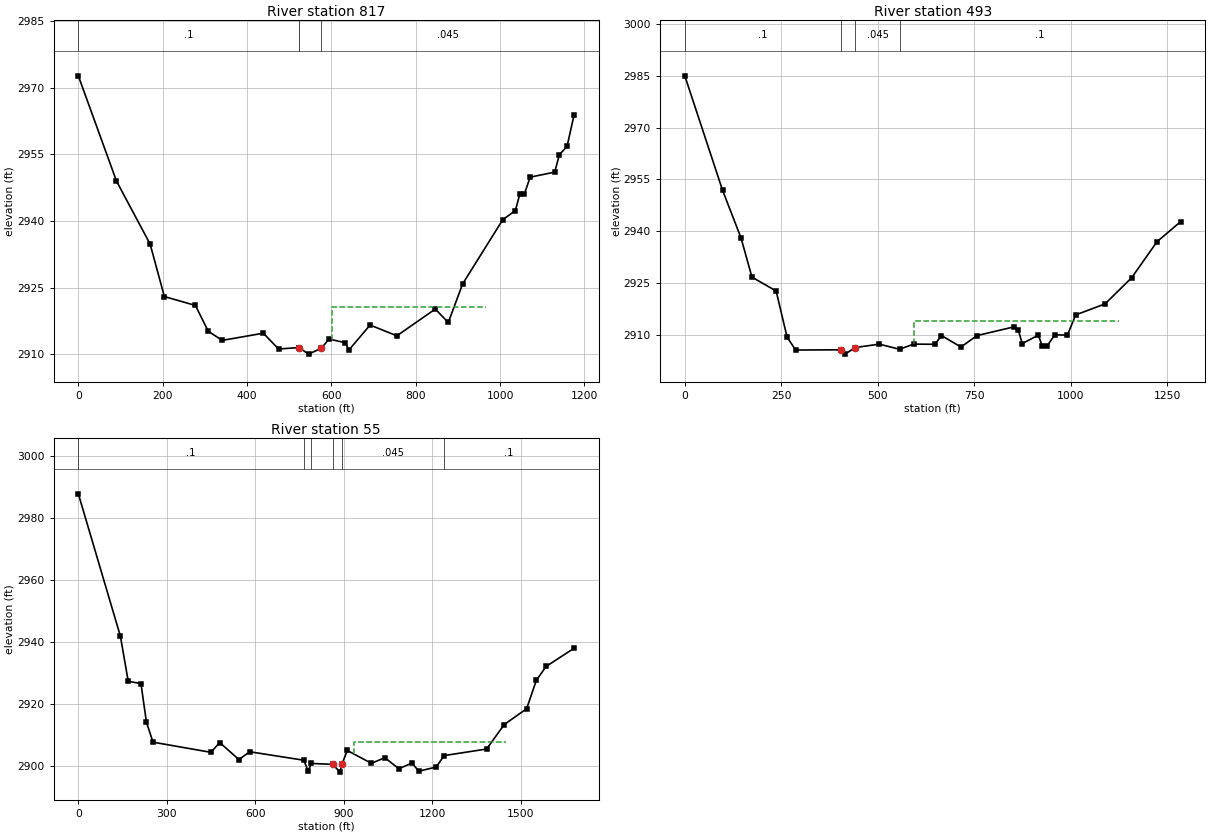
Type RM Length L Ch R = 1 ,817     ,324.2,324.2,324.2
XS GIS Cut Line= 5
2088020.64457217379591.3153856972087689.45328371379528.633570889
2087609.58121651379579.9905692972087376.26465355380036.538155234
2087230.51845375380215.861563495
#Sta/Elev= 30
       0 2972.69    90.4 2949.01   170.3  2934.8     204    2923   277.7    2921
   308.1 2915.17   341.5 2913.14   438.7 2914.75   474.9 2911.19   523.4 2911.52
   523.7  2911.5   545.9 2910.04   576.52911.368   594.4 2913.44   633.4  2912.6
   641.3 2910.93   691.9 2916.59   755.3 2914.16   846.5 2920.19   877.3 2917.16
   911.4 2925.86  1006.7 2940.33  1036.3 2942.33  1047.1 2946.12  1057.4 2945.99
  1071.4 2949.88  1129.7 2951.01  1140.7 2954.95  1158.9 2956.79  1175.8 2963.97
#Mann= 4 ,-1 , 0
       0      .1       0   523.4      .1       0   523.7    .045       0
   576.5    .045       0
#XS Ineff= 1 ,-1
  600.81   967.72920.737
Permanent Ineff=
       F
Bank Sta=523.7,576.5
XS Rating Curve= 0 ,0
Exp/Cntr=0.5,0.3

Type RM Length L Ch R = 1 ,493     ,414.8,414.8,414.8
XS GIS Cut Line= 4
2088076.05326353379598.3535230112087764.40836593379448.173648841
2087438.70563574379469.7874710282087246.56694691380050.640418599
#Sta/Elev= 30
       0 2985.01    97.7 2951.88   145.6 2938.05   173.9 2926.69   236.6 2922.66
   264.9 2909.32     287 2905.57   405.1 2905.63   414.9 2904.38   441.72906.296
   503.7 2907.27   556.3 2905.79   592.5 2907.28     648 2907.23   664.8 2909.77
   715.2 2906.44   756.7 2909.75   853.4  2912.3   863.8 2911.29   874.1 2907.44
   915.6 2909.88     926  2906.7   937.5  2906.6   958.3 2909.97   990.9 2909.89
  1012.4 2915.75  1088.4 2918.93  1157.5 2926.53    1223 2936.95  1284.2 2942.76
#Mann= 4 ,-1 , 0
       0      .1       0   405.1    .045       0   441.7    .045       0
   556.3      .1       0
#XS Ineff= 1 ,-1
  594.55  1123.3 2913.91
Permanent Ineff=
       F
Bank Sta=405.1,441.7
XS Rating Curve= 0 ,0
Exp/Cntr=0.3,0.1

Type RM Length L Ch R = 1 ,55      ,,,
XS GIS Cut Line= 4
2088122.84145608379589.2930047632087457.22313095379212.587894228
2087186.93697903379425.1962674612087240.38179268379995.929517974
#Sta/Elev= 30
       0 2987.68   142.7 2941.75   169.2 2927.24   212.5 2926.47   230.9 2914.09
   253.3 2907.59   449.5 2904.32   479.7 2907.46   544.7 2901.98   581.4  2904.5
   764.8 2901.77   779.6 2898.28   790.2 2900.73   863.3 2900.43   887.4 2897.93
  894.01 2900.45   912.3 2904.92   994.1 2900.76  1039.6 2902.59  1087.4 2899.02
  1131.7 2900.88  1154.8 2898.24  1214.1 2899.57  1240.5 2903.26  1384.9 2905.38
  1444.8 2913.28  1520.6 2918.36  1553.5 2927.49  1586.5    2932  1681.9  2937.9
#Mann= 6 ,-1 , 0
       0      .1       0   764.8    .045       0   790.2      .1       0
   863.3    .045       0  894.01    .045       0  1240.5      .1       0
#XS Ineff= 1 ,-1
  934.14  1450.3 2907.52
Permanent Ineff=
       F
Bank Sta=863.3,894.01
XS Rating Curve= 0 ,0
Exp/Cntr=0.3,0.1
LCMann Table=0

Chan Stop Cuts=-1
Use User Specified Reach Order=0
Composite Channel Slope=5